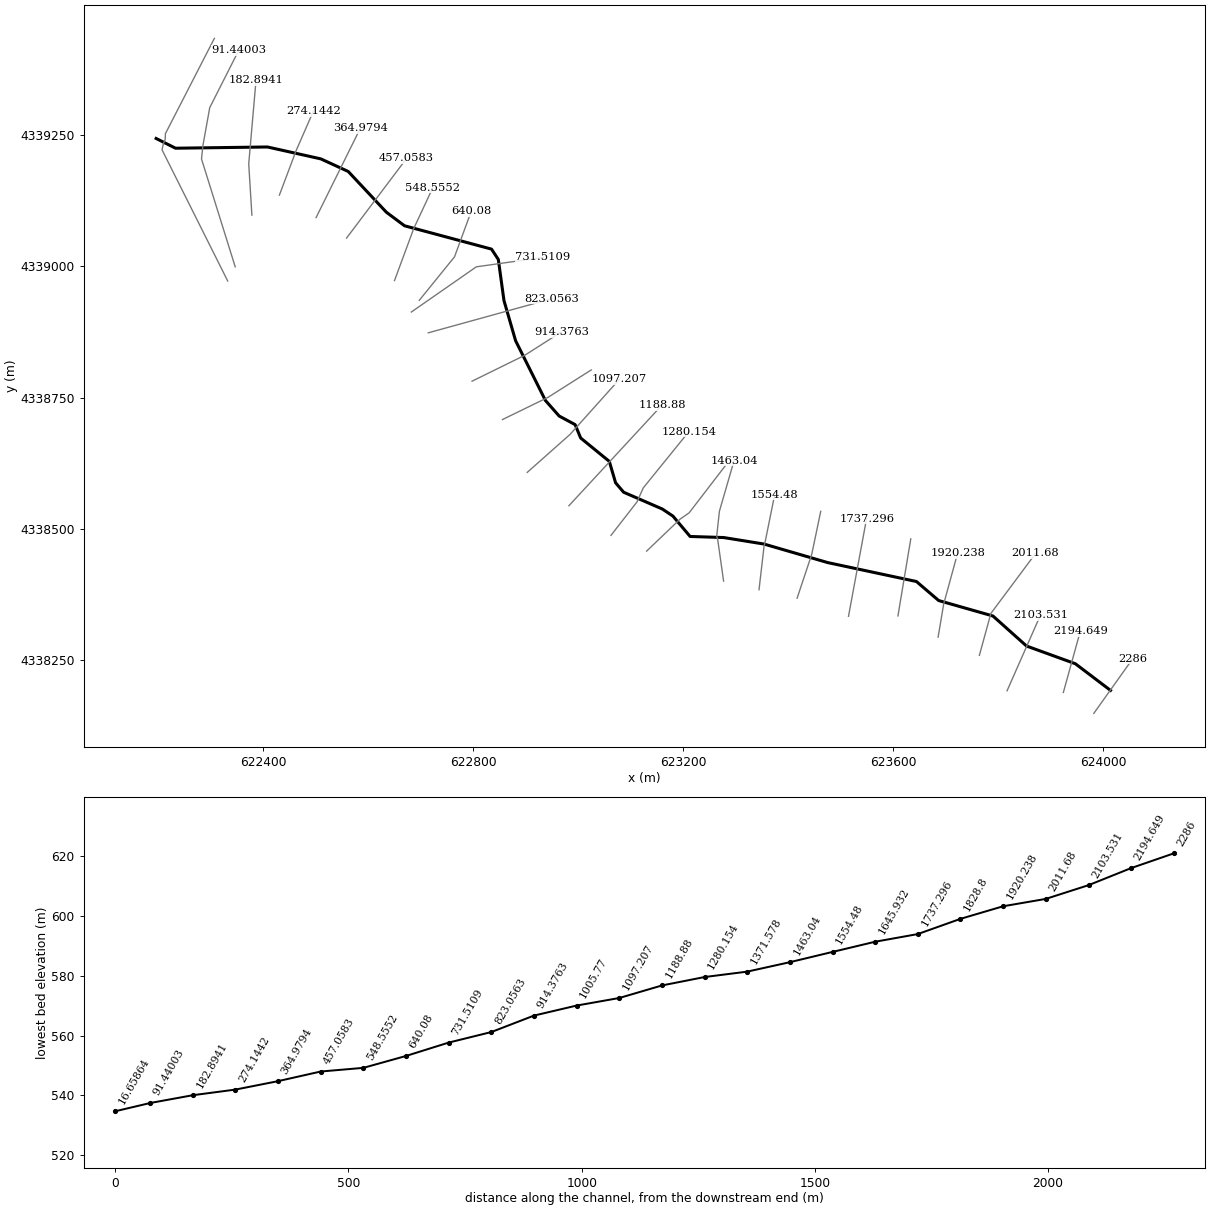
--- LaurelRunHrs.prj (project) ---

Proj Title=LaurelRunHrs
Current Plan=p01
Default Exp/Contr=0.3,0.1
SI Units
Geom File=g01
Flow File=f01
Plan File=p01
Y Axis Title=Elevation
X Axis Title(PF)=Main Channel Distance
X Axis Title(XS)=Station
BEGIN DESCRIPTION:
September 2018
Tucker County ABFE Study
US Army Corps of Engineers, Pittsburgh District
NAD 1983 UTM 17N (meters)
END DESCRIPTION:
DSS Export Rating Curves= 0
DSS Export Rating Curve Sorted= 0
DSS Export Volume Flow Curves= 0
DXF OffsetX= 0
DXF OffsetY= 0
DXF ScaleX= 1
DXF ScaleY= 10

--- LaurelRunHrs.p01 (plan) ---

Plan Title=LaurelRunHrs_plan
Program Version=5.05
Short Identifier=Plan1_subcritical
Geom File=g01
Flow File=f01
Subcritical Flow
K Sum by GR= 0
Std Step Tol= 0.003
Critical Tol= 0.003
Num of Std Step Trials= 20
Max Error Tol= 0.1
Flow Tol Ratio= 0.001
Split Flow NTrial= 30
Split Flow Tol= 0.006
Split Flow Ratio= 0.02
Log Output Level= 0
Friction Slope Method= 1
Unsteady Friction Slope Method= 2
Unsteady Bridges Friction Slope Method= 1
Parabolic Critical Depth
Global Vel Dist= 0 , 0 , 0
Global Log Level= 0
CheckData=True
Encroach Param=-1 ,0,0, 0
Computation Interval=1MIN
Output Interval=1HOUR
Instantaneous Interval=1HOUR
Mapping Interval=1HOUR
Computation Time Step Use Courant=        0
Computation Time Step Use Time Series=    0
Computation Time Step Count To Double=0
Computation Time Step Max Doubling=0
Computation Time Step Max Halving=0
Computation Time Step Residence Courant=0
Run HTab= 0
Run UNet= 0
Run Sediment= 0
Run PostProcess= 0
Run WQNet= 0
Run RASMapper=-1
UNET Theta= 1
UNET Theta Warmup= 1
UNET ZTol= 0.006
UNET ZSATol= 0.006
UNET MxIter= 20
UNET Max Iter WO Improvement= 0
UNET MaxInSteps= 0
UNET DtIC= 0
UNET DtMin= 0
UNET MaxCRTS= 20
UNET WFStab= 2
UNET SFStab= 1
UNET WFX= 1
UNET SFX= 1
UNET 1D Methodology=Finite Difference
UNET DSS MLevel= 4
UNET Pardiso=0
UNET DZMax Abort= 30
UNET Use Existing IB Tables=-1
UNET Froude Reduction=False
UNET Froude Limit= 0.8
UNET Froude Power= 4
UNET D1 Cores= 0
UNET D2 Coriolis=0
UNET D2 Cores= 0
UNET D2 Theta= 1
UNET D2 Theta Warmup= 1
UNET D2 Z Tol= 0.003
UNET D2 Volume Tol= 0.003
UNET D2 Max Iterations= 20
UNET D2 Equation= 0
UNET D2 RampUpFraction=0.1
UNET D2 TimeSlices= 1
UNET D2 BCVolumeCheck=0
UNET D1D2 MaxIter= 0
UNET D1D2 ZTol=0.003
UNET D1D2 QTol=0.1
UNET D1D2 MinQTol=0.03
Write IC File= 0
Write IC File at Fixed DateTime=0
Write IC File at Sim End=0
Echo Input=False
Echo Parameters=False
Echo Output=False
Write Detailed= 0
HDF Write Warmup=0
HDF Write Time Slices=0
HDF Flush=0
HDF Face Node Velocities=0
HDF Compression= 1
HDF Chunk Size= 1
HDF Spatial Parts= 1
HDF Use Max Rows=0
HDF Fixed Rows= 1
Calibration Method= 0
Calibration Iterations= 20
Calibration Max Change=0.05
Calibration Tolerance=0.2
Calibration Maximum=1.5
Calibration Minimum=0.5
Calibration Optimization Method= 1
WQ AD Non Conservative
WQ ULTIMATE=-1
WQ Max Comp Step=1HOUR
WQ Output Interval=15MIN
WQ Output Selected Increments= 0
WQ Output face flow=0
WQ Output face velocity=0
WQ Output face area=0
WQ Output face dispersion=0
WQ Output cell volume=0
WQ Output cell surface area=0
WQ Output cell continuity=0
WQ Output cumulative cell continuity=0
WQ Output face conc=0
WQ Output face dconc_dx=0
WQ Output face courant=0
WQ Output face peclet=0
WQ Output face adv mass=0
WQ Output face disp mass=0
WQ Output cell mass=0
WQ Output cell source sink temp=0
WQ Output nsm pathways=0
WQ Output nsm derived pathways=0
WQ Output MaxMinRange=-1
WQ Daily Max Min Mean=-1
WQ Daily Range=0
WQ Daily Time=0
WQ Create Restart=0
WQ Fixed Restart=0
WQ System Summary=0
WQ Write To DSS=0
WQ Use Fixed Temperature=0
Sorting and Armoring Iterations= 10
XS Update Threshold= 0.02
Bed Roughness Predictor= 0
Hydraulics Update Threshold= 0.02
Energy Slope Method= 1
Volume Change Method= 1
Sediment Retention Method= 0
XS Weighting Method= 0
Number of US Weighted Cross Sections= 1
Number of DS Weighted Cross Sections= 1
Upstream XS Weight=0
Main XS Weight=1
Downstream XS Weight=0
Number of DS XS's Weighted with US Boundary= 1
Upstream Boundary Weight= 1
Weight of XSs Associated with US Boundary= 0
Number of US XS's Weighted with DS Boundary= 1
Downstream Boundary Weight= 0.5
Weight of XSs Associated with DS Boundary= 0.5
Percentile Method= 0
Sediment Output Level= 4
Mass or Volume Output= 0
Output Increment Type= 1
Profile and TS Output Increment= 1
XS Output Flag= 0
XS Output Increment= 10
Write Gradation File= 0
Read Gradation Hotstart= 0
Write HDF5 File= 1
Write Binary Output= 1
Write DSS Sediment File= 0
SV Curve= 0
Specific Gage Flag= 0

--- LaurelRunHrs.f01 (steady flow) ---

Flow Title=LaurelRunHrs_flow
Program Version=5.05
Number of Profiles= 1
Profile Names=PF 1
River Rch & RM=Laurel Run (Hrs),1               ,2286
   14.64
River Rch & RM=Laurel Run (Hrs),1               ,1737.296
 17.6412
River Rch & RM=Laurel Run (Hrs),1               ,1371.578
 19.9915
River Rch & RM=Laurel Run (Hrs),1               ,16.65864
 21.3507
Boundary for River Rch & Prof#=Laurel Run (Hrs),1               , 1
Up Type= 2
Dn Type= 1
Dn Known WS=536
DSS Import GetInterval= 0
DSS Import GetPeak= 0
DSS Import FillOption= 0

--- LaurelRunHrs.g01 (geometry) ---

Geom Title=LaurelRunHrs_geometry
Program Version=5.05

River Reach=Laurel Run (Hrs),1
Reach XY= 30
      624014.133    4338192.8523     623947.1492    4338243.6083
     623854.1524    4338277.3471     623790.1958    4338334.4873
     623686.8208    4338363.9057     623644.4716     4338400.116
     623475.5726    4338436.1371     623354.1286    4338471.4591
     623277.3256    4338483.8232     623213.4208    4338485.8688
     623180.6938    4338524.6404     623160.4532    4338538.1342
623086.7917933314338570.09280933623071.4918746654338588.00890933
623059.4974946554338628.81597865623004.9472106574338673.32384132
622994.4553999834338698.74818398622963.9592466484338715.16341066
     622937.9094     4338744.652     622881.0526     4338858.413
622858.9079253354338934.80121334622848.1177645644339013.16582148
622835.1763646674339032.88604989     622669.45684339077.31884801
     622634.9152    4339103.0869622562.2715399964339180.65304933
622509.952911997  4339204.692784622408.448490667  4339227.303416
622233.3286239954339224.95561067      622196.358    4339243.5021

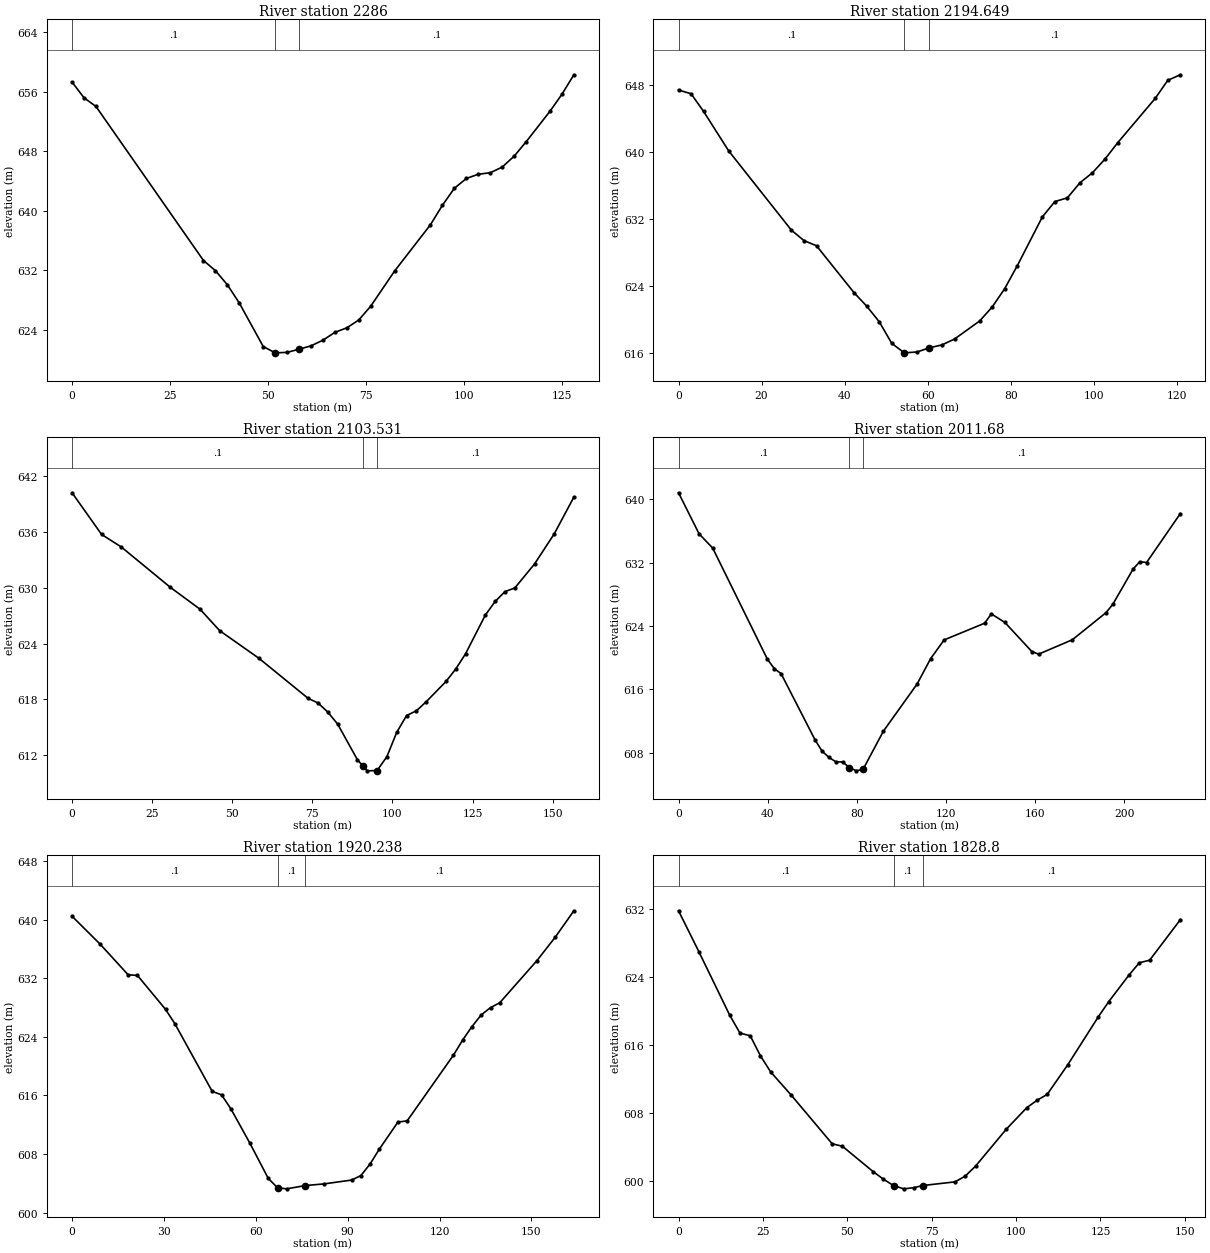
Type RM Length L Ch R = 1 ,2286    ,90.2,91.35,92.42
XS GIS Cut Line= 2
     623982.3077    4338149.1082     624056.6316    4338253.4476
#Sta/Elev= 30
       0  657.27    3.05  655.16     6.1     654   33.55  633.32    36.6  631.96
   39.65  630.06    42.7  627.61    48.8  621.78   51.85  620.93    54.9  620.99
   57.95  621.42      61  621.87   64.05  622.63    67.1  623.68   70.15  624.29
    73.2  625.34   76.25   627.2   82.35  631.92    91.5  638.13   94.55  640.74
    97.6  643.02  100.65  644.33   103.7   644.9  106.75   645.1   109.8  645.86
  112.85  647.32   115.9  649.25     122  653.35  125.05  655.63   128.1  658.25
#Mann= 3 , 0 , 0
       0      .1       0   51.85      .1       0   57.95      .1       0
Bank Sta=51.85,57.95
XS Rating Curve= 0 ,0
Exp/Cntr=0.3,0.1

Type RM Length L Ch R = 1 ,2194.649,91.63,91.12,90.61
XS GIS Cut Line= 2
     623924.2649    4338188.8681     623956.5343    4338305.3072
#Sta/Elev= 30
       0  647.46    3.02  647.01    6.04  644.89   12.08  640.17   27.19  630.68
   30.21  629.44   33.23  628.82   42.29  623.19   45.31   621.6   48.33  619.73
   51.35  617.14   54.37  616.01   57.39  616.11   60.41  616.61   63.43  616.96
   66.46  617.66    72.5  619.82   75.52  621.49   78.54  623.69   81.56  626.42
    87.6  632.27   90.62  634.11   93.64  634.56   96.66  636.36   99.68  637.56
   102.7   639.2  105.72  641.13  114.79  646.46  117.81  648.62  120.83  649.28
#Mann= 3 , 0 , 0
       0      .1       0   54.37      .1       0   60.41      .1       0
Bank Sta=54.37,60.41
XS Rating Curve= 0 ,0
Exp/Cntr=0.3,0.1

Type RM Length L Ch R = 1 ,2103.531,91.33,91.85,91.94
XS GIS Cut Line= 2
     623817.1084    4338192.1754     623880.3765    4338335.4611
#Sta/Elev= 30
       0  640.22    9.21  635.74   15.36  634.39   30.71  630.04   39.93   627.7
   46.07  625.39   58.35  622.41   73.71   618.1   76.78  617.61   79.85  616.62
   82.92  615.33   89.07   611.5   90.87   610.8   92.14  610.31   95.21  610.34
   98.28  611.84  101.35  614.46  104.42  616.26  107.49  616.77  110.56  617.75
  116.71  619.92  119.78  621.27  122.85  622.92  128.99  627.06  132.06  628.53
  135.13  629.59   138.2  629.98  144.35  632.56  150.49  635.79  156.63  639.75
#Mann= 3 , 0 , 0
       0      .1       0   90.87      .1       0   95.21      .1       0
Bank Sta=90.87,95.21
XS Rating Curve= 0 ,0
Exp/Cntr=0.3,0.1

Type RM Length L Ch R = 1 ,2011.68 ,91.44,91.44,95.14
XS GIS Cut Line= 3
     623764.3526    4338259.5922     623786.2893    4338339.4172
     623871.3481     4338453.452
#Sta/Elev= 30
       0  640.84     9.2  635.66   15.33  633.85   39.86  619.81   42.93  618.63
   45.99  617.99   61.32  609.57   64.39   608.2   67.45  607.41   70.52  606.86
   73.59  606.83   76.65  606.13   79.72  605.71   82.78  605.91   91.87  610.72
     107  616.68  113.05  619.88  119.11  622.25  137.27  624.36   140.3  625.54
  146.35  624.46  158.46  620.78  161.48  620.45  176.62  622.27  191.75   625.7
  194.78  626.75  203.86   631.2  206.89  632.14  209.91  632.03  225.05  638.21
#Mann= 3 , 0 , 0
       0      .1       0   76.65      .1       0   82.78      .1       0
Bank Sta=76.65,82.78
XS Rating Curve= 0 ,0
Exp/Cntr=0.3,0.1

Type RM Length L Ch R = 1 ,1920.238,94.61,91.44,89.09
XS GIS Cut Line= 3
     623685.7425    4338294.2497     623696.4072    4338357.4218
     623722.7843    4338453.6614
#Sta/Elev= 30
       0  640.45    9.15  636.65    18.3  632.47   21.36  632.37   30.51  627.75
   33.56  625.79   45.76  616.55   48.81  616.08   51.86  614.17   57.96  609.56
   64.07  604.67   67.09   603.4   70.11  603.25   76.16   603.7   82.21  603.92
   91.28  604.45   94.31  605.06   97.33  606.65  100.35  608.68   106.4  612.36
  109.42  612.53  124.54   621.5  127.57  623.58  130.59   625.4  133.62     627
  136.64  627.98  139.66  628.65  151.76  634.38  157.81  637.62  163.85   641.2
#Mann= 3 , 0 , 0
       0      .1       0   67.09      .1       0   76.16      .1       0
Bank Sta=67.09,76.16
XS Rating Curve= 0 ,0
Exp/Cntr=0.3,0.1

Type RM Length L Ch R = 1 ,1828.8  ,91.57,91.5,93.33
XS GIS Cut Line= 2
     623609.2657    4338334.6669     623633.7037    4338481.2964
#Sta/Elev= 30
       0  631.75    6.07   626.9   15.17  619.46    18.2  617.36   21.24  617.05
   24.27  614.68    27.3  612.79   33.37  610.07   45.51  604.34   48.54  604.05
   57.64  601.07   60.67  600.18   63.71  599.42   66.74  599.04   69.78  599.18
   72.35  599.43   81.91  599.86   84.94  600.54   87.98  601.71   97.08  606.05
  103.15  608.58  106.18  609.45  109.21  610.15  115.28  613.62  124.38  619.29
  127.42  621.05  133.48  624.21  136.52  625.64  139.55  625.93  148.65   630.7
#Mann= 3 , 0 , 0
       0      .1       0   63.71      .1       0   72.35      .1       0
Bank Sta=63.71,72.35
XS Rating Curve= 0 ,0
Exp/Cntr=0.3,0.1

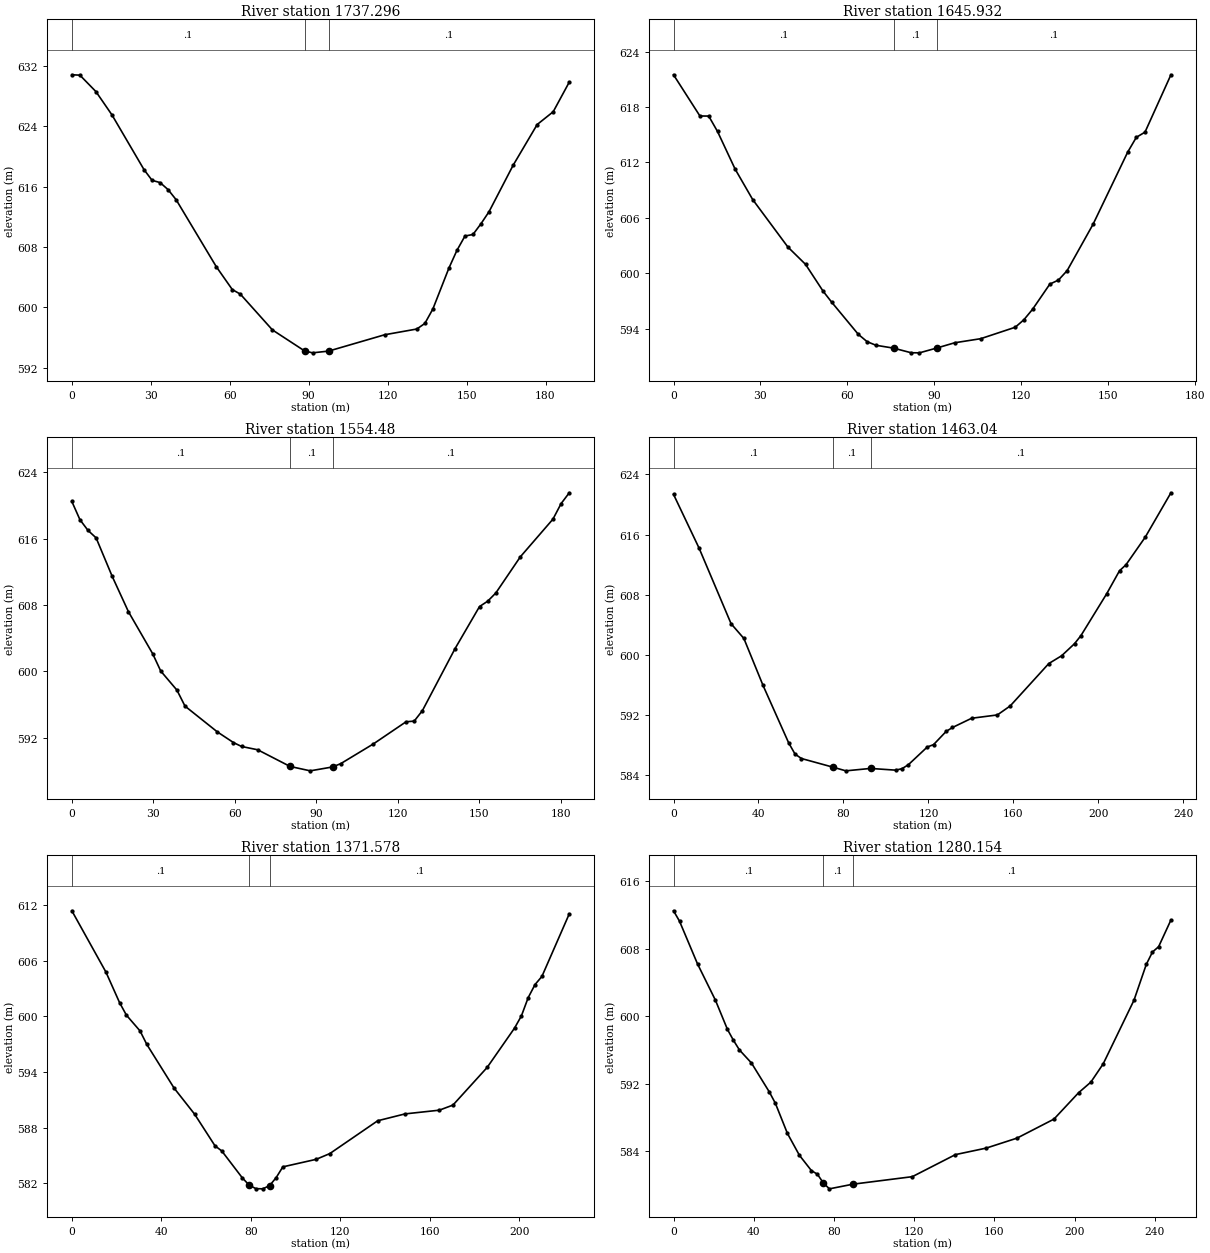
Type RM Length L Ch R = 1 ,1737.296,91.85,91.36,90.23
XS GIS Cut Line= 2
     623515.0859    4338333.9372     623549.4818    4338519.8074
#Sta/Elev= 30
       0  630.83    3.05  630.78    9.15   628.6   15.24  625.51   27.44  618.24
   30.49  616.83   33.54  616.53   36.59  615.59   39.63  614.26   54.88  605.38
   60.98  602.34   64.02  601.74   76.22  596.99   88.42  594.21   91.46  593.95
   97.56  594.18   118.9  596.35   131.1  597.11  134.15  597.85   137.2  599.77
  143.29  605.19  146.34  607.54  149.39  609.44  152.44  609.65  155.49  611.08
  158.54  612.67  167.68  618.82  176.83  624.23  182.93  625.93  189.03  629.86
#Mann= 3 , 0 , 0
       0      .1       0   88.42      .1       0   97.56      .1       0
Bank Sta=88.42,97.56
XS Rating Curve= 0 ,0
Exp/Cntr=0.3,0.1

Type RM Length L Ch R = 1 ,1645.932,90.99,91.45,91.98
XS GIS Cut Line= 3
     623417.1899    4338368.3331     623445.0731    4338451.8764
     623462.1692    4338533.6981
#Sta/Elev= 30
       0  621.49    9.11  617.03   12.15  617.02   15.19  615.35   21.26  611.28
   27.33  607.98   39.48  602.84   45.56  600.97   51.63  598.06   54.67  596.84
   63.78  593.39   66.81   592.6   69.85  592.21   75.93   591.9      82   591.4
   84.88  591.39   91.06  591.93   97.03  592.48  105.99  592.92  117.93  594.16
  120.91  594.97   123.9   596.1  129.87  598.83  132.85  599.27  135.84  600.29
  144.79  605.31  156.74  613.12  159.72  614.72  162.71  615.28  171.66  621.49
#Mann= 3 , 0 , 0
       0      .1       0   75.93      .1       0   91.06      .1       0
Bank Sta=75.93,91.06
XS Rating Curve= 0 ,0
Exp/Cntr=0.3,0.1

Type RM Length L Ch R = 1 ,1554.48 ,88.4,91.44,93
XS GIS Cut Line= 4
     623344.6498    4338384.4287     623354.2244    4338467.2203
      623355.931    4338473.6787     623374.4155    4338565.0072
#Sta/Elev= 30
       0  620.48    2.98  618.28    5.95  616.99    8.93  616.09   14.88  611.43
   20.84  607.18   29.77  602.11   32.74  600.02    38.7  597.72   41.67  595.79
   53.58  592.68   59.53  591.39   62.51  590.92   68.46  590.52   80.37  588.51
    87.8  587.98   96.04  588.45   99.04  588.85  111.06  591.23  123.09   593.9
  126.09  593.98   129.1  595.24  141.12  602.72  150.14   607.8  153.15  608.45
  156.15  609.44  165.17   613.8  177.19  618.35   180.2  620.23   183.2  621.53
#Mann= 3 , 0 , 0
       0      .1       0   80.37      .1       0   96.04      .1       0
Bank Sta=80.37,96.04
XS Rating Curve= 0 ,0
Exp/Cntr=0.3,0.1

Type RM Length L Ch R = 1 ,1463.04 ,95.18,91.46,75.76
XS GIS Cut Line= 5
     623277.1809    4338400.9652     623266.1838    4338478.4686
     623264.0839    4338486.7136     623269.2154    4338533.9216
     623297.0247    4338629.8302
#Sta/Elev= 30
       0  621.35   12.04  614.19    27.1  604.13   33.12  602.17   42.15  595.91
   54.19  588.28    57.2  586.78   60.22  586.19   75.27  585.02   81.12  584.55
   92.72  584.87   104.6  584.64  107.56  584.84  110.53  585.36  119.43  587.72
   122.4  588.04  128.34   589.8  131.31  590.32  140.33  591.55  152.43  591.99
  158.48  593.19  176.64  598.83  182.69  599.87  188.74  601.47  191.77  602.55
  203.87  608.11  209.92  611.18  212.95  611.97  222.03  615.65  234.13  621.56
#Mann= 3 , 0 , 0
       0      .1       0   75.27      .1       0   92.72      .1       0
Bank Sta=75.27,92.72
XS Rating Curve= 0 ,0
Exp/Cntr=0.3,0.1

Type RM Length L Ch R = 1 ,1371.578,90.98,91.42,96.39
XS GIS Cut Line= 4
     623130.6015     4338457.983     623194.4528    4338519.0171
     623211.5642    4338530.8758     623280.4882    4338620.5698
#Sta/Elev= 30
       0  611.37   15.23  604.76   21.32  601.47   24.37  600.12   30.46  598.42
    33.5  596.96   45.69  592.25   54.83  589.45   63.96  586.03   67.01  585.47
   76.15  582.58   79.19   581.8   82.24  581.41   85.28  581.39   88.33  581.73
    91.3   582.6   94.28  583.76  109.15  584.57  115.26  585.19  136.66  588.73
  148.89  589.47  164.18  589.87  170.29  590.42  185.58  594.48  197.81  598.72
  200.87  600.03  203.92  602.01  206.98  603.42  210.04  604.29  222.27  611.04
#Mann= 3 , 0 , 0
       0      .1       0   79.19      .1       0   88.33      .1       0
Bank Sta=79.19,88.33
XS Rating Curve= 0 ,0
Exp/Cntr=0.3,0.1

Type RM Length L Ch R = 1 ,1280.154,91.58,91.27,83.75
XS GIS Cut Line= 4
      623062.696    4338487.9736     623112.2753    4338551.6551
     623124.1599    4338578.2779     623211.1276    4338685.6177
#Sta/Elev= 30
       0  612.48    2.99  611.25   11.96   606.2   20.92  601.89    26.9  598.44
   29.89  597.15   32.88  596.01   38.86  594.47   47.83  591.02   50.81  589.69
   56.79  586.14   62.77  583.55   68.75  581.74   71.74  581.31   74.73  580.27
   77.72  579.58   89.45  580.13  119.07  581.02  140.56  583.63  155.91   584.4
  171.26  585.58  189.68  587.83  201.96  590.95   208.1  592.21  214.24  594.37
  229.59   601.9  235.73  606.14   238.8   607.6  241.87  608.23  248.01  611.39
#Mann= 3 , 0 , 0
       0      .1       0   74.73      .1       0   89.45      .1       0
Bank Sta=74.73,89.45
XS Rating Curve= 0 ,0
Exp/Cntr=0.3,0.1

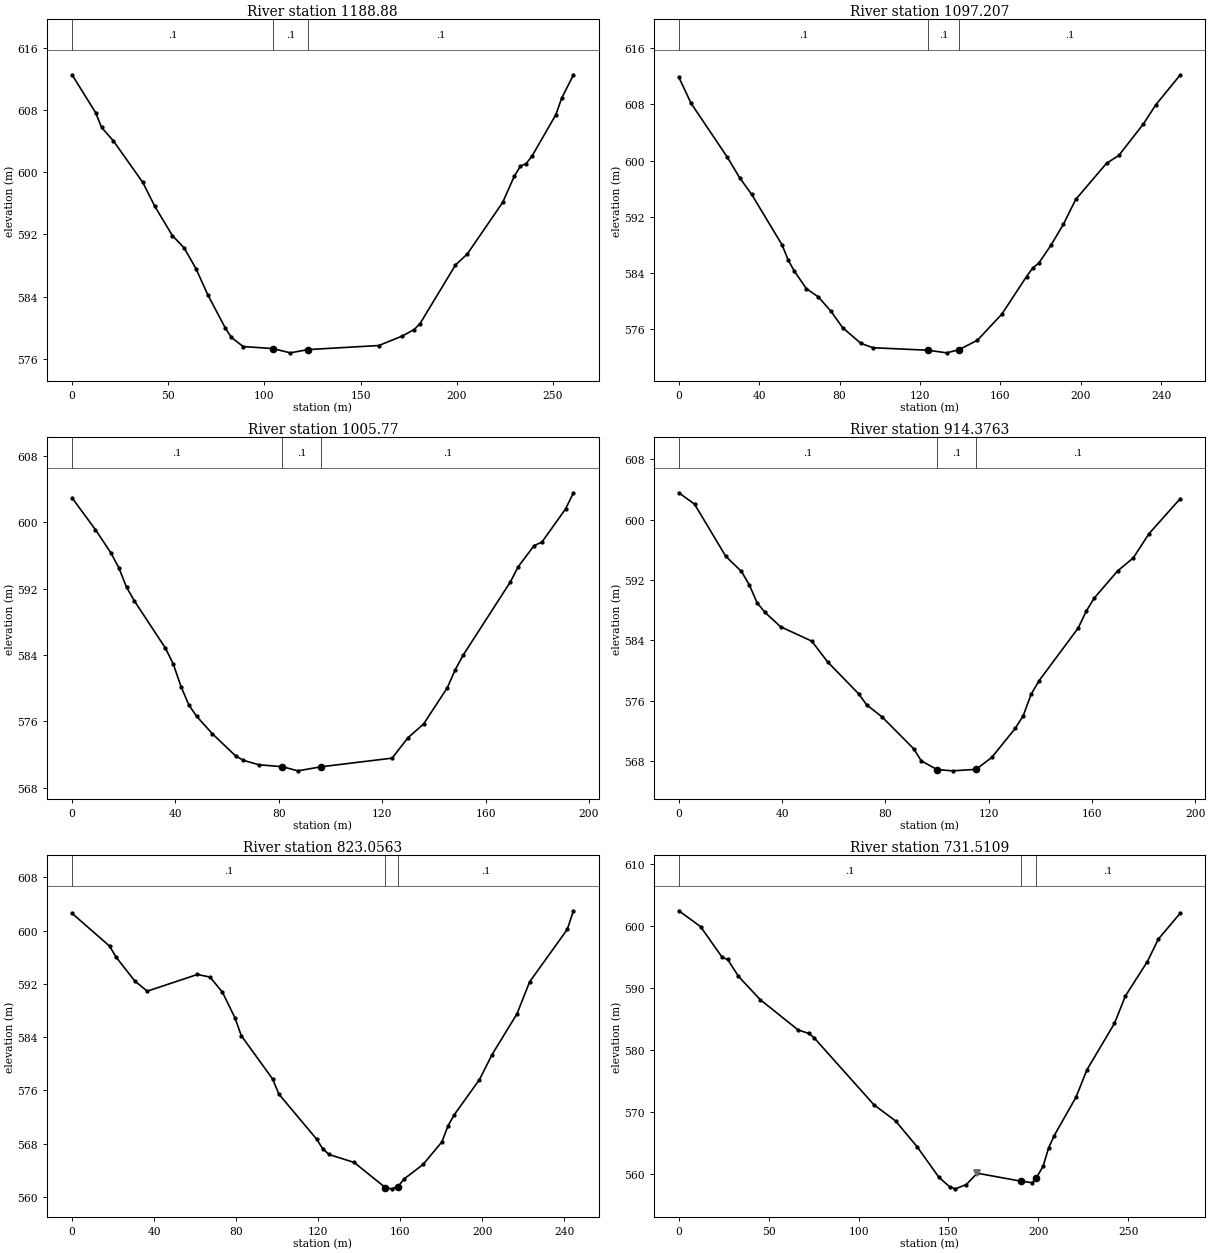
Type RM Length L Ch R = 1 ,1188.88 ,94.04,91.67,91.93
XS GIS Cut Line= 2
     622982.5271    4338544.3299     623159.5337    4338735.6241
#Sta/Elev= 30
       0  612.53   12.26  607.66   15.33  605.76   21.46  604.04   36.79  598.68
   42.93  595.65   52.12  591.86   58.26  590.26   64.39  587.61   70.52  584.25
   79.72  579.93   82.79  578.76   88.92  577.58  104.25  577.32  113.45  576.77
  122.65  577.19  159.44  577.71  171.71  578.94  177.84  579.77   180.9  580.54
   199.3  588.07  205.43  589.48  223.83  596.12  229.96  599.54  233.03  600.76
  236.09  601.12  239.16  602.11  251.43  607.38  254.49  609.52  260.62  612.53
#Mann= 3 , 0 , 0
       0      .1       0  104.25      .1       0  122.65      .1       0
Bank Sta=104.25,122.65
XS Rating Curve= 0 ,0
Exp/Cntr=0.3,0.1

Type RM Length L Ch R = 1 ,1097.207,93.39,91.44,82.82
XS GIS Cut Line= 3
      622903.152    4338607.8301     622984.5258    4338679.9761
     623078.5711    4338784.8367
#Sta/Elev= 30
       0  611.87    6.04  608.18   24.17  600.45   30.21  597.56   36.25  595.16
   51.35  587.97   54.38  585.82    57.4  584.25   63.44  581.73   69.48  580.53
   75.52  578.56   81.56  576.14   90.63  573.91   96.67   573.3  124.06  572.94
  133.25  572.57  139.37  573.01  148.56  574.36  160.81  578.11  173.05  583.46
  176.12  584.67  179.18  585.38   185.3  587.97  191.43  590.93  197.55  594.46
  212.86  599.61  218.99  600.73  231.23  605.23  237.36  607.94  249.61  612.24
#Mann= 3 , 0 , 0
       0      .1       0  124.06      .1       0  139.37      .1       0
Bank Sta=124.06,139.37
XS Rating Curve= 0 ,0
Exp/Cntr=0.3,0.1

Type RM Length L Ch R = 1 ,1005.77 ,91.38,91.39,91.33
XS GIS Cut Line= 3
     622856.0031    4338708.4248      622942.645    4338750.6305
     623025.0722    4338802.8813
#Sta/Elev= 30
       0  602.92    9.04  599.09   15.06  596.28   18.07  594.51   21.08  592.16
   24.09  590.52   36.14  584.81   39.15  582.91   42.16  580.19   45.18  577.98
   48.19  576.61   54.21  574.53   63.25  571.84   66.26  571.31   72.28  570.77
   81.32  570.54   87.34  570.04   96.37  570.53  123.82  571.57  129.92  574.02
  136.02  575.69  145.17  580.05  148.22  582.21  151.27  583.96  169.57   592.8
  172.62  594.64  178.72  597.16  181.77  597.59  190.92  601.59  193.97  603.53
#Mann= 3 , 0 , 0
       0      .1       0   81.32      .1       0   96.37      .1       0
Bank Sta=81.32,96.37
XS Rating Curve= 0 ,0
Exp/Cntr=0.3,0.1

Type RM Length L Ch R = 1 ,914.3763,91.98,91.32,90.52
XS GIS Cut Line= 3
     622798.0593      4338781.45     622898.6826    4338830.8829
     622967.9221    4338875.1127
#Sta/Elev= 30
       0  603.58    6.06  602.07   18.18  595.14   24.24  593.14   27.27  591.36
    30.3  588.98   33.33  587.72   39.39  585.81   51.51  583.89   57.57  581.16
   69.69  576.89   72.72  575.45   78.78  573.82    90.9  569.64   93.93  568.01
   99.99  566.86  106.05  566.69  115.15  566.89  121.24  568.48  130.37  572.36
  133.41  574.01  136.45  576.84   139.5  578.63  154.71  585.64  157.75  587.83
   160.8  589.56  169.93   593.2  176.01  594.93   182.1  598.14  194.27  602.82
#Mann= 3 , 0 , 0
       0      .1       0   99.99      .1       0  115.15      .1       0
Bank Sta=99.99,115.15
XS Rating Curve= 0 ,0
Exp/Cntr=0.3,0.1

Type RM Length L Ch R = 1 ,823.0563,92,91.55,91.09
XS GIS Cut Line= 2
     622714.7153    4338873.5252     622950.4596    4338938.6128
#Sta/Elev= 30
       0  602.59   18.34  597.65    21.4  596.04   30.57  592.43   36.68  590.89
   61.14   593.4   67.26  593.01   73.37  590.73   79.48  586.87   82.54   584.2
   97.83  577.69  100.88  575.42  119.23  568.68  122.28  567.21  125.34  566.35
  137.57  565.16  152.85  561.37  155.91  561.19  158.97  561.53  162.02  562.69
   171.2  564.85  180.37  568.24  183.42  570.68  186.48  572.35  198.71  577.61
  204.82  581.34  217.05  587.51  223.17  592.29  241.51  600.16  244.56  602.97
#Mann= 3 , 0 , 0
       0      .1       0  152.85      .1       0  158.97      .1       0
Bank Sta=152.85,158.97
XS Rating Curve= 0 ,0
Exp/Cntr=0.3,0.1

Type RM Length L Ch R = 1 ,731.5109,87.52,91.43,95.34
XS GIS Cut Line= 3
     622682.4361    4338913.1069     622806.2162    4338999.1517
     622933.2616    4339017.0884
#Sta/Elev= 30
       0  602.49   12.06  599.93   24.12  594.97   27.13  594.64   33.16  591.91
   45.22  588.17   66.33  583.28   72.36  582.71   75.37  581.97  108.54  571.21
   120.6   568.6  132.66  564.41  144.72  559.51  150.75  557.97   153.8  557.66
  159.91  558.35  166.02  560.18  190.46  558.89  196.57  558.65  198.78  559.35
  202.68  561.31  205.74  564.25  208.79  566.21  221.01  572.45  227.12  576.88
   242.4  584.34  248.51  588.77  260.72  594.31  266.83  597.93  279.05  602.12
#Mann= 3 , 0 , 0
       0      .1       0  190.46      .1       0  198.78      .1       0
Levee=-1,166.04,560.21,0,,,,
Bank Sta=190.46,198.78
XS Rating Curve= 0 ,0
Exp/Cntr=0.3,0.1

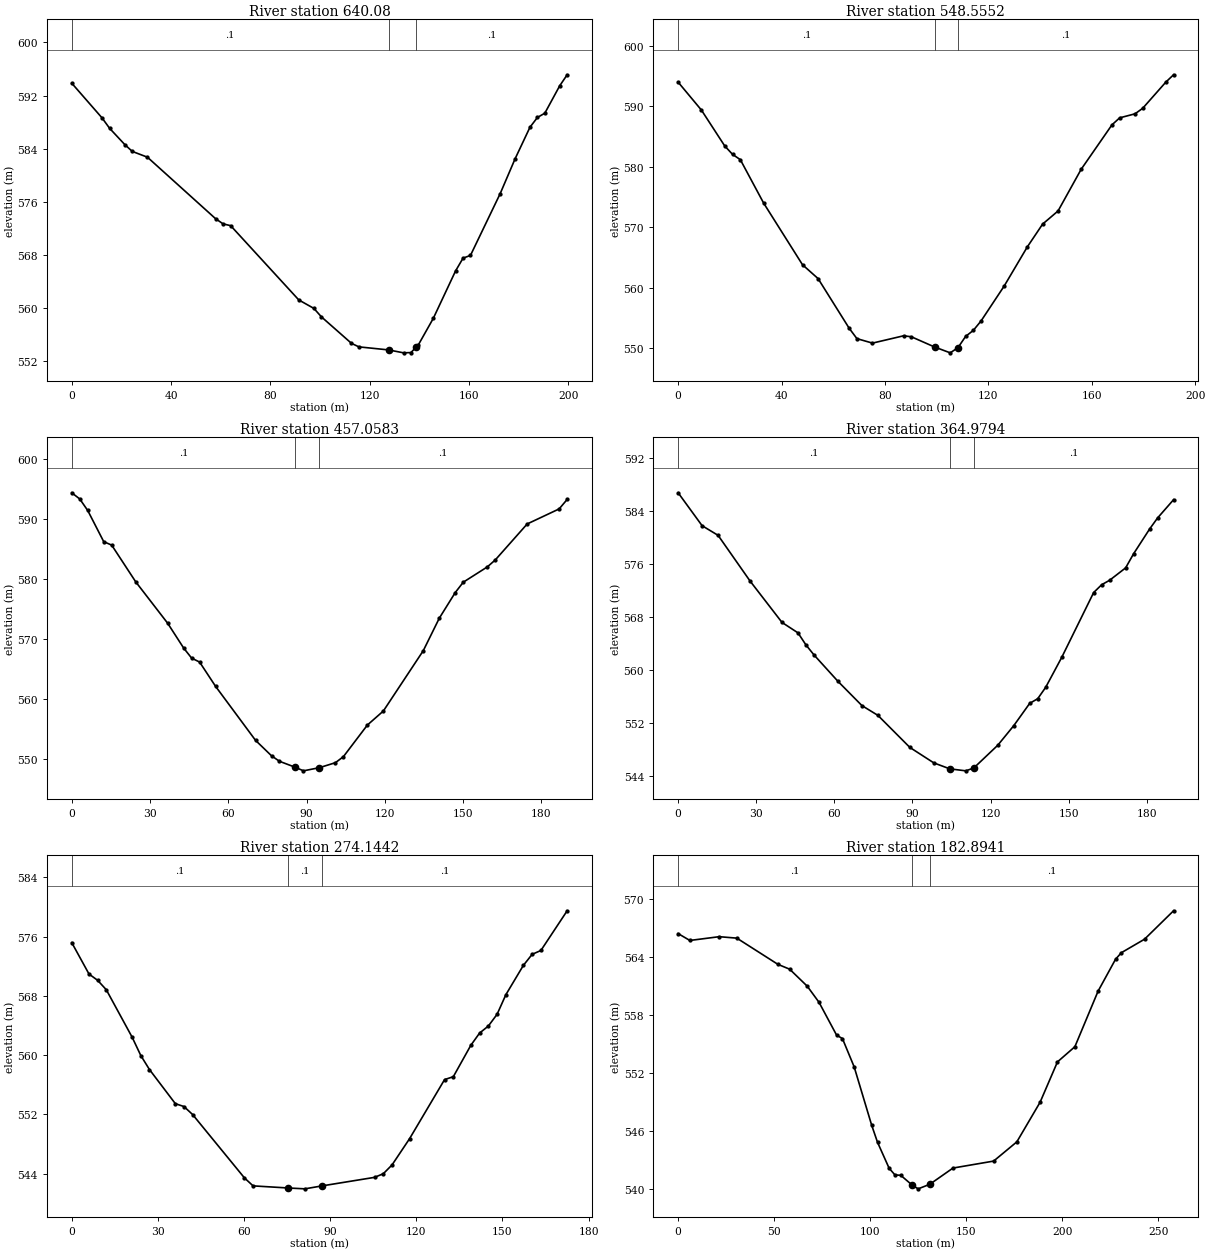
Type RM Length L Ch R = 1 ,640.08  ,91.8,91.52,91.23
XS GIS Cut Line= 3
     622697.5174     4338935.332     622764.6929    4339018.2003
     622796.7264    4339105.3618
#Sta/Elev= 30
       0  593.86   12.19  588.63   15.24  587.06   21.34  584.61   24.38  583.57
   30.48   582.7   57.91  573.43   60.96  572.64   64.01  572.37   91.44  561.17
   97.53  559.89  100.58  558.61  112.67  554.62  115.66  554.09  127.64  553.63
  133.64  553.19  136.63  553.23  138.59  554.01  139.63  554.41  145.62  558.39
   154.6  565.55   157.6  567.47   160.6  567.89  172.58  577.22  178.57  582.46
  184.56  587.22  187.56  588.69  190.55  589.34  196.54  593.47  199.54  595.13
#Mann= 3 , 0 , 0
       0      .1       0  127.64      .1       0  138.59      .1       0
Bank Sta=127.64,138.59
XS Rating Curve= 0 ,0
Exp/Cntr=0.3,0.1

Type RM Length L Ch R = 1 ,548.5552,93.82,91.5,90.35
XS GIS Cut Line= 3
     622650.3685    4338972.9558     622686.8621    4339071.6772
     622723.3937    4339149.9624
#Sta/Elev= 30
       0  594.01    9.02  589.38   18.04  583.44   21.05  582.06   24.06  581.18
   33.08  573.99   48.11  563.79   54.13   561.5   66.16  553.28   69.16  551.56
   75.18  550.82   87.21  552.03   90.21  551.87   99.24  550.17  105.25  549.21
  108.23  550.06  111.21  551.93  114.19  552.93  117.17  554.48   126.1  560.25
  135.04  566.72     141  570.52  146.96  572.69  155.89  579.58  167.81  586.94
  170.79   588.1  176.75  588.77  179.72  589.69  188.66  594.02  191.64  595.23
#Mann= 3 , 0 , 0
       0      .1       0   99.24      .1       0  108.23      .1       0
Bank Sta=99.24,108.23
XS Rating Curve= 0 ,0
Exp/Cntr=0.3,0.1

Type RM Length L Ch R = 1 ,457.0583,89.56,92.08,93.64
XS GIS Cut Line= 2
     622559.0871    4339053.9184     622673.3873     4339205.525
#Sta/Elev= 30
       0  594.35    3.06  593.32    6.12   591.4   12.25   586.2   15.31  585.62
    24.5  579.51   36.75   572.6   42.87  568.47   45.94  566.78      49  566.12
   55.12  562.07   70.43  553.07   76.56  550.49   79.62  549.57   85.75  548.56
   88.81  547.98   94.93  548.51  101.06  549.34  104.12  550.35  113.31  555.62
  119.43  557.96  134.74  568.03  140.87  573.44  146.99  577.72  150.06  579.44
  159.24  581.98   162.3  583.14  174.55  589.15   186.8  591.66  189.87  593.24
#Mann= 3 , 0 , 0
       0      .1       0   85.75      .1       0   94.93      .1       0
Bank Sta=85.75,94.93
XS Rating Curve= 0 ,0
Exp/Cntr=0.3,0.1

Type RM Length L Ch R = 1 ,364.9794,90.54,90.84,92.2
XS GIS Cut Line= 2
     622500.9845    4339092.8123     622585.4844    4339263.3379
#Sta/Elev= 30
       0   586.8    9.21  581.82   15.35  580.36   27.63  573.45    39.9  567.19
   46.04  565.61   49.11  563.78   52.18  562.28   61.39  558.28    70.6  554.61
   76.74  553.13   89.02  548.28   98.23  545.94  104.37  545.04   110.5  544.74
  113.57  545.17  122.78  548.61  128.92  551.57  135.06  554.95  138.13  555.65
   141.2  557.38  147.34  561.89  159.62  571.71  162.69  572.89  165.76  573.57
   171.9  575.44  174.97  577.58   181.1  581.31  184.17  582.99  190.31  585.75
#Mann= 3 , 0 , 0
       0      .1       0  104.37      .1       0  113.57      .1       0
Bank Sta=104.37,113.57
XS Rating Curve= 0 ,0
Exp/Cntr=0.3,0.1

Type RM Length L Ch R = 1 ,274.1442,87.83,91.25,91.52
XS GIS Cut Line= 3
     622431.1344    4339135.6749     622462.8936    4339220.1099
      622495.901    4339295.5393
#Sta/Elev= 30
       0  575.18    6.01  570.94    9.02  570.09   12.03  568.82   21.05   562.4
   24.06  559.93   27.06  558.05   36.08  553.44   39.09  553.05    42.1  551.97
   60.14  543.42   63.15  542.34   75.18  542.06   81.19  541.94    87.2  542.34
  105.46  543.49  108.51  543.98  111.56  545.17  117.66  548.71  129.85  556.69
   132.9  557.08     139  561.32  142.05  562.97   145.1  563.92  148.15  565.51
   151.2  568.15   157.3  572.11  160.35   573.6   163.4  574.12  172.55  579.48
#Mann= 3 , 0 , 0
       0      .1       0   75.18      .1       0    87.2      .1       0
Bank Sta=75.18,87.2
XS Rating Curve= 0 ,0
Exp/Cntr=0.3,0.1

Type RM Length L Ch R = 1 ,182.8941,91.09,91.45,88.59
XS GIS Cut Line= 3
     622378.7468    4339097.5748     622372.7331    4339195.1751
     622386.6843    4339354.7503
#Sta/Elev= 30
       0  566.46    6.11  565.75   21.39  566.14   30.56  565.99   51.95  563.28
   58.06  562.78   67.23  561.02   73.34  559.36   82.51  555.96   85.56   555.6
   91.67  552.67  100.81  546.62  103.83  544.87  109.87  542.19   112.9   541.5
  115.92  541.46  121.96  540.43  124.99  540.06  131.03  540.53  143.12  542.21
  164.28  542.93  176.37  544.92  188.46  549.01  197.52  553.19  206.59  554.76
  218.68  560.51  227.75   563.8  230.77  564.48  242.86  565.88  257.97  568.82
#Mann= 3 , 0 , 0
       0      .1       0  121.96      .1       0  131.03      .1       0
Bank Sta=121.96,131.03
XS Rating Curve= 0 ,0
Exp/Cntr=0.3,0.1

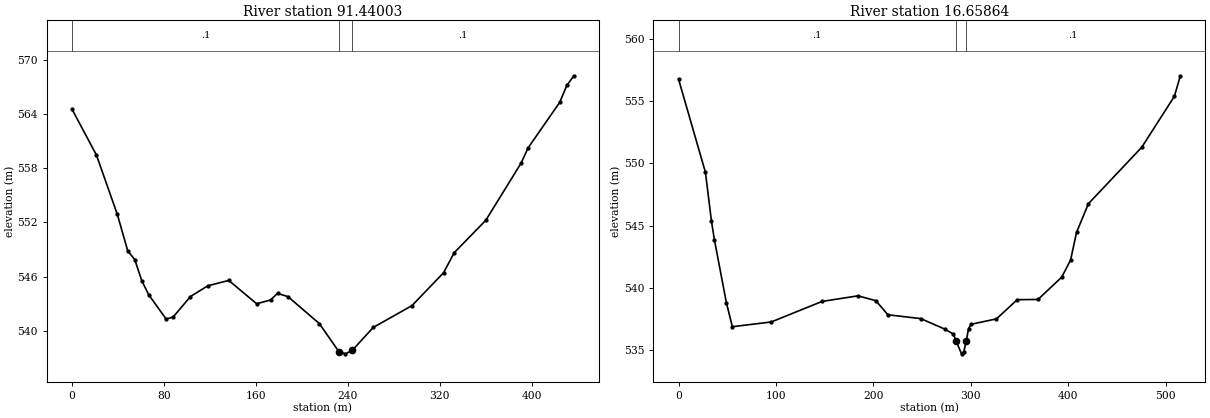
Type RM Length L Ch R = 1 ,91.44003,75.9,74.78,74.95
XS GIS Cut Line= 5
     622346.9967    4338999.1496     622282.7834    4339204.5482
     622285.4388    4339229.9221      622298.478    4339302.2312
     622353.8804     4339411.588
#Sta/Elev= 30
       0   564.5   21.22  559.44    39.4  552.87    48.5  548.83   54.56  547.88
   60.62  545.56   66.68  543.99   81.84  541.31    87.9  541.51  103.05  543.79
  118.21  544.98   136.4  545.57  160.64  542.99  172.77  543.41  178.83  544.14
  187.92  543.78   215.2   540.8  232.21   537.7  237.88  537.45  243.78  537.82
  262.14  540.37  295.82  542.78  323.38  546.42  332.58  548.63  360.16  552.23
  390.81  558.54  396.94  560.23  424.52  565.28  430.65  567.14  436.78  568.21
#Mann= 3 , 0 , 0
       0      .1       0  232.21      .1       0  243.78      .1       0
Bank Sta=232.21,243.78
XS Rating Curve= 0 ,0
Exp/Cntr=0.3,0.1

Type RM Length L Ch R = 1 ,16.65864,3.61,16.66,6.8
XS GIS Cut Line= 6
     622332.7092     4338972.162     622207.6338    4339221.8786
      622209.949    4339232.7927      622213.587    4339241.7224
     622214.0896    4339252.7556     622307.3091    4339434.1255
#Sta/Elev= 30
       0  556.77   27.62  549.28   33.76  545.38   36.83  543.86   49.11  538.81
   55.24  536.88   95.14  537.26  147.32  538.91  184.15  539.36  202.56  538.97
  214.84  537.84   248.6  537.53  273.15  536.69  282.08  536.29  284.87  535.74
  290.45   534.7  292.86  534.88  295.27  535.72  297.68  536.71  300.09  537.07
  326.35  537.51  347.66  539.05  368.96  539.07  393.31  540.86  402.44  542.24
  408.53  544.46   420.7  546.76  475.49   551.3  508.97  555.39  515.06  557.04
#Mann= 3 , 0 , 0
       0      .1       0  284.87      .1       0  295.27      .1       0
Bank Sta=284.87,295.27
XS Rating Curve= 0 ,0
Exp/Cntr=0.3,0.1
LCMann Table=0

Chan Stop Cuts=-1
Use User Specified Reach Order=0
Composite Channel Slope=5